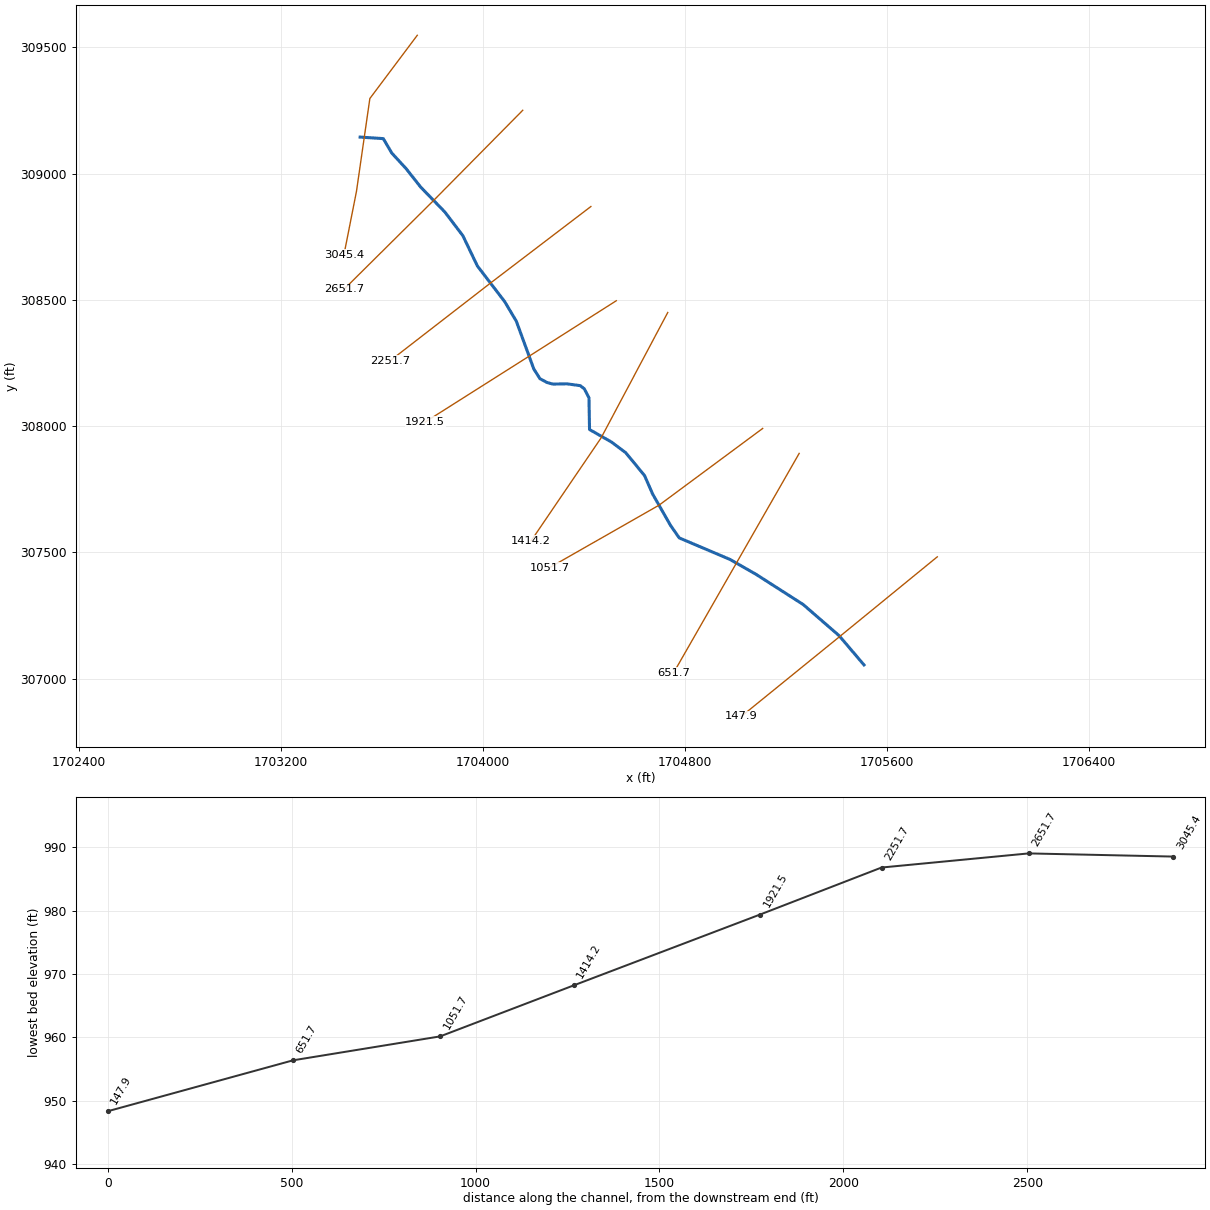
--- FlagRn.prj (project) ---

Proj Title=FlagRn
Current Plan=p01
Default Exp/Contr=0,0
English Units
Geom File=g01
Flow File=f01
Plan File=p01
BEGIN DESCRIPTION:
END DESCRIPTION:
DSS Export Rating Curves= 0
DSS Export Rating Curve Sorted= 0
DSS Export Volume Flow Curves= 0
DXF OffsetX= 0
DXF OffsetY= 0
DXF ScaleX= 0
DXF ScaleY= 0

--- FlagRn.p01 (plan) ---

Plan Title=Floodplain
Program Version=4.00
Geom File=g01
Flow File=f01
K Sum by GR=0
Std Step Tol=0.01
Critical Tol=0.01
Num of Std Step Trials=20
Max Error Tol=0.3
Flow Tol Ratio=0.001
Split Flow NTrial=30
Split Flow Tol=0.02
Split Flow Ratio=0.02
Log Output Level=0
Friction Slope Method=1
Unsteady Friction Slope Method=2
Unsteady Bridges Friction Slope Method=1
Global Log Level=0
CheckData=False
Run HTab=0
Run UNet=0
Run PostProcess=0
UNET Theta=0
UNET Theta Warmup=0
UNET ZTol=0
UNET ZSATol=0
UNET MxIter=0
UNET MaxInSteps=0
UNET DtIC=0
UNET DtMin=0
UNET MaxCRTS=0
UNET WFStab=0
UNET SFStab=0
UNET WFX=0
UNET SFX=0
UNET DSS MLevel=0
UNET DZMax Abort=0
UNET Convert EG Bridges=0
UNET Use Existing IB Tables=0
UNET Froude Limit=0
UNET Froude Power=0
Write IC File=0
Echo Input=False
Echo Output=False
Write Detailed=0

--- FlagRn.f01 (steady flow) ---

Flow Title=NFF Regression Equation
Program Version=4.00
Number of Profiles=1
Profile Names=P100yr
River Rch & RM=FlagRn,Main      ,3045.4
877.9868
River Rch & RM=FlagRn,Main      ,147.9
936.6864
Boundary for River Rch & Prof#=FlagRn,Main      ,1
Up Type=0
Dn Type=3
Dn Slope=0.014138

--- FlagRn.g01 (geometry) ---

Geom Title=USGS 3m DEM
Program Version=4.00

River Reach=FlagRn          ,Main
Reach XY= 30
     1703514.421       309144.83       1703606.1      309138.829
     1703639.701      309081.708     1703697.061      309019.311
     1703754.182      308946.831     1703849.941       308848.19
      1703921.22      308754.349      1703978.82      308634.349
     1704086.581      308493.708     1704132.902       308415.95
     1704202.022      308226.831       1704226.5       308188.19
     1704255.062      308172.828     1704277.381       308166.83
      1704333.78      308167.789     1704385.861      308160.589
     1704401.942      308148.349     1704420.662      308112.348
     1704422.823      307986.828     1704509.221       307937.63
     1704566.341       307894.91     1704640.741      307804.429
     1704672.422      307731.949     1704743.461      307607.389
     1704778.019       307557.71       1704978.9       307472.51
     1705083.302      307412.751      1705268.82       307293.95
     1705411.142      307170.588     1705509.619      307054.737

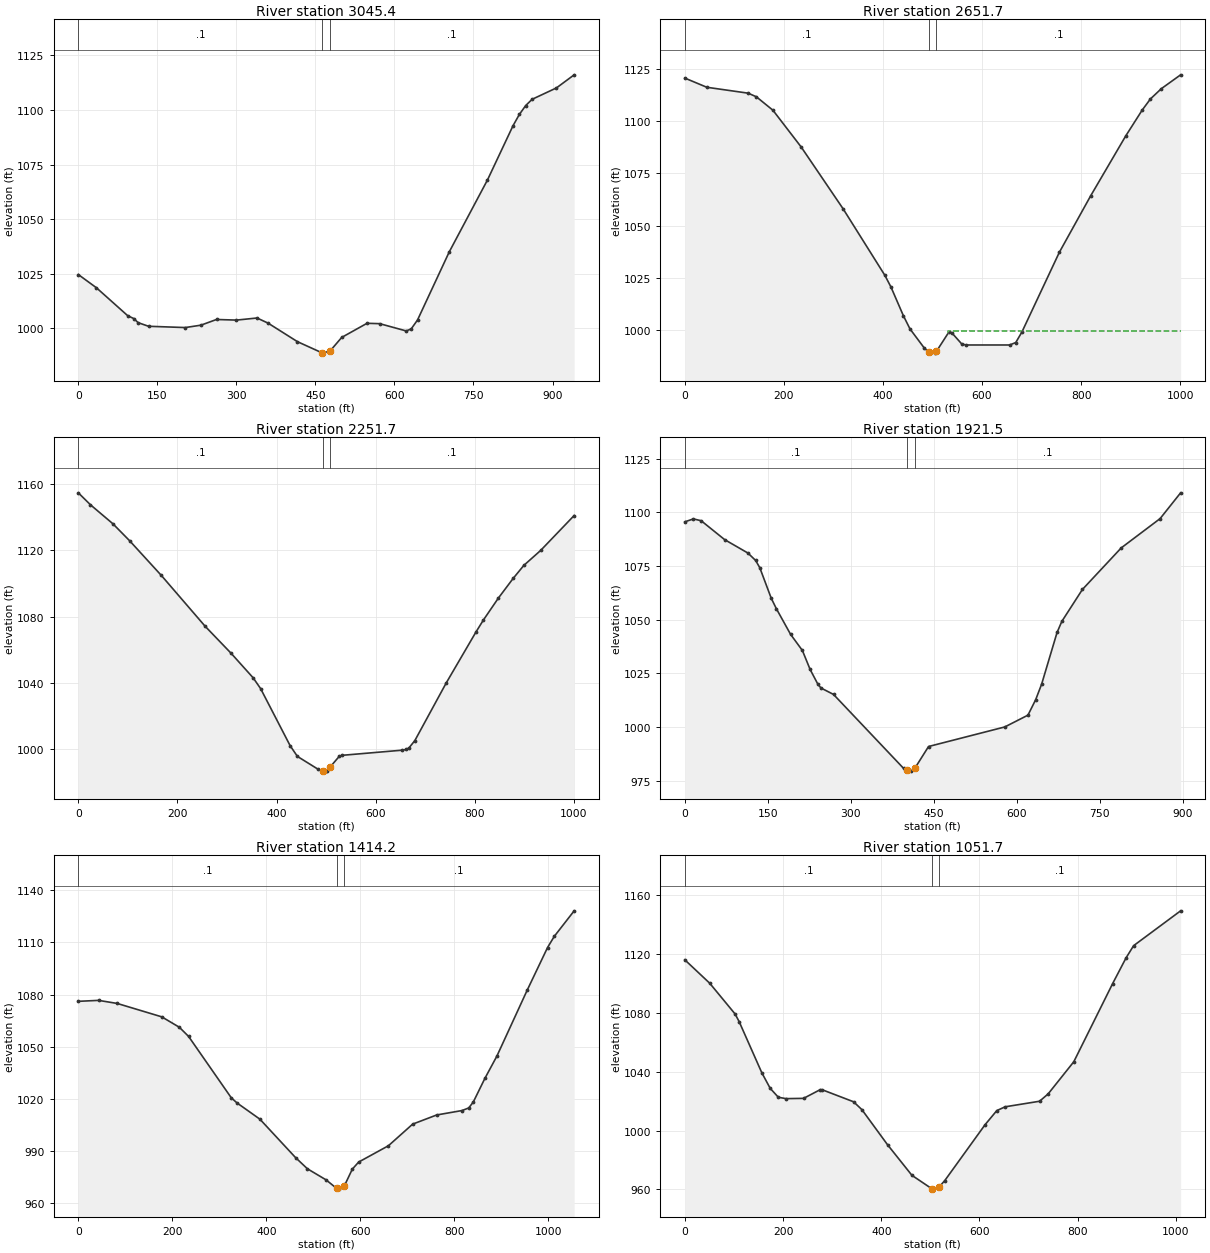
Type RM Length L Ch R = 1 ,3045.4  ,408.698,393.637,378.35
XS GIS Cut Line= 4
     1703740.729      309548.018     1703552.953      309297.649
     1703499.991      308930.121     1703450.238      308678.148
#Sta/Elev= 30
       0 1024.58    34.3 1018.53    93.7 1005.72   105.2 1004.41   113.5 1002.53
   133.2 1000.87   202.9 1000.28   232.6 1001.37   262.3 1003.98   300.2  1003.7
   339.2 1004.66   360.2  1002.3   415.9  993.81   463.1  988.64   463.9  988.56
   478.1  989.62   499.9  995.76   547.9 1002.23   571.9 1002.07   622.3  998.73
   631.8  999.66   643.8 1003.75     704 1034.96   776.6 1067.95     825 1092.77
   837.1 1097.98   849.2 1102.06   861.3 1104.91   907.5 1110.13   941.1 1116.13
#Mann= 3 , 0 , 0
       0      .1       0   463.1    .045       0   478.1      .1       0
Bank Sta=463.1,478.1
XS Rating Curve= 0 ,0
Exp/Cntr=0.3,0.1

Type RM Length L Ch R = 1 ,2651.7  ,403.147,400,397.251
XS GIS Cut Line= 3
     1704158.376      309251.043     1703806.558      308895.067
     1703451.165      308542.609
#Sta/Elev= 30
       0 1120.47    44.4 1116.08   127.8 1113.26   144.5 1111.52   177.9  1105.1
     235 1087.51   319.4 1058.06   403.9  1026.2   416.1 1020.66   441.3 1006.88
   454.5 1000.64   483.3  991.52     493  989.43   495.1  989.06   505.1  989.17
     508  989.93   533.7  999.37   538.6  998.86   558.9  993.46   567.3  992.95
   655.6  992.95     668  994.11   680.5  999.17     756 1037.23   819.1 1064.16
   889.7 1092.71   923.2 1105.17   939.9 1110.51   961.8 1115.39  1000.8 1122.02
#Mann= 3 , 0 , 0
       0      .1       0     493    .045       0     508      .1       0
#XS Ineff= 2 , 0
                          530.38          999.49
Permanent Ineff=
       F       F
Bank Sta=493,508
XS Rating Curve= 0 ,0
Exp/Cntr=0.3,0.1

Type RM Length L Ch R = 1 ,2251.7  ,332.019,330.182,328.134
XS GIS Cut Line= 3
     1704428.258      308869.943     1704030.194      308566.524
     1703634.474      308260.089
#Sta/Elev= 30
       0 1154.68    24.5 1147.46    69.7 1136.04   103.4 1125.82   167.6 1104.84
   255.8 1074.25   308.2 1057.96   352.9 1043.09   367.9 1036.62   427.6 1002.13
   442.2  995.71   484.6  987.84     493  987.19   500.5  986.83   502.2     987
     508  989.24   526.9  995.83   532.3  996.36   652.4  999.43   662.3  999.92
   667.4 1000.86   679.2 1005.23   742.5 1039.98   802.6 1070.74   817.6 1077.96
   847.6  1091.1   877.6 1103.03   899.3 1110.94   933.1 1119.91  1000.8    1141
#Mann= 3 , 0 , 0
       0      .1       0     493    .045       0     508      .1       0
Bank Sta=493,508
XS Rating Curve= 0 ,0
Exp/Cntr=0.3,0.1

Type RM Length L Ch R = 1 ,1921.5  ,494.268,507.309,518.315
XS GIS Cut Line= 3
     1704528.748      308496.791     1704186.526      308279.092
     1703771.916      308016.453
#Sta/Elev= 30
       0 1095.55    15.6 1096.91    29.6 1096.06    71.9 1087.28   114.1 1081.01
   128.1 1077.55   135.6 1074.16   156.3 1059.93   165.4 1055.15   191.2 1043.15
   212.6 1035.61   226.6 1026.76   240.7 1019.85   246.2 1018.13   268.9 1015.14
   395.5   980.7     401  979.97   409.6  979.41     416  980.78   440.7  990.88
   578.5  999.99   620.4 1005.49   634.4 1012.72   645.1 1019.91     673    1044
   681.6 1049.15   718.8 1064.03     789  1083.4   859.3 1097.05   896.4 1109.06
#Mann= 3 , 0 , 0
       0      .1       0     401    .045       0     416      .1       0
Bank Sta=401,416
XS Rating Curve= 0 ,0
Exp/Cntr=0.3,0.1

Type RM Length L Ch R = 1 ,1414.2  ,372.575,362.509,351.662
XS GIS Cut Line= 3
     1704732.574      308450.248     1704468.723      307953.884
     1704191.467      307546.116
#Sta/Elev= 30
       0 1076.15    43.1  1076.7    82.8 1074.93   177.6 1067.23   214.9 1061.26
   234.6    1056   325.5  1020.7   337.8 1017.73   386.4 1008.42   462.2  986.36
   487.5  979.91   527.2  973.54   549.7  968.64   554.1  968.21   564.7  969.94
   567.9  971.08   583.1  979.71   596.6  983.77     660  993.16   711.5 1005.57
   762.6 1010.83   816.6 1013.38   830.9 1014.88   840.7 1018.36   865.1 1031.81
   890.8 1044.69   955.5  1082.7   998.6 1107.08    1013 1113.53  1055.2 1128.17
#Mann= 3 , 0 , 0
       0      .1       0   549.7    .045       0   564.7      .1       0
Bank Sta=549.7,564.7
XS Rating Curve= 0 ,0
Exp/Cntr=0.3,0.1

Type RM Length L Ch R = 1 ,1051.7  ,390.375,400,412.316
XS GIS Cut Line= 3
     1705108.521      307991.177     1704697.959      307687.172
     1704264.785      307440.123
#Sta/Elev= 30
       0 1116.21    50.7 1100.29   102.5  1079.3   110.6 1074.19   156.9 1039.28
   173.9 1028.74   190.4  1022.7   205.9 1021.74   241.8 1021.93   275.7 1027.85
   279.8 1027.78   343.6 1019.61   360.6 1014.25   412.7  990.41   462.4  969.57
   503.4  960.33   504.9  960.17   515.8  960.82   518.4  961.86   529.4  966.03
   611.4 1004.03   635.3 1013.63   652.4  1016.2   722.3 1019.97   739.7 1024.94
     792 1046.85   871.1 1100.04   898.5 1117.58   913.8 1125.83  1009.5 1149.54
#Mann= 3 , 0 , 0
       0      .1       0   503.4    .045       0   518.4      .1       0
Bank Sta=503.4,518.4
XS Rating Curve= 0 ,0
Exp/Cntr=0.3,0.1

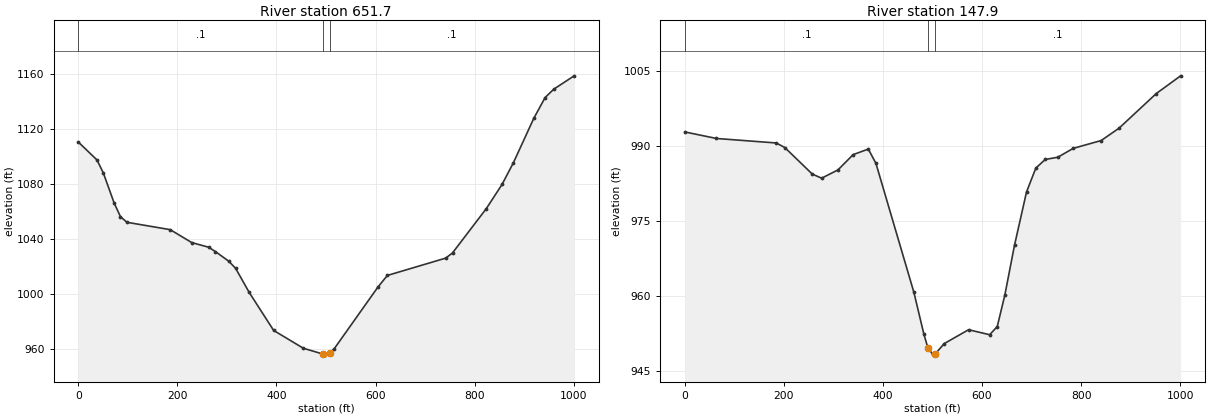
Type RM Length L Ch R = 1 ,651.7   ,512.048,503.799,495.485
XS GIS Cut Line= 3
     1705252.977      307892.321     1705004.345      307457.946
     1704755.712       307023.57
#Sta/Elev= 30
       0 1110.36    37.6 1097.39    50.3 1088.09    72.4 1066.01      85 1056.23
    98.1 1052.11   185.5 1046.76     229 1037.38   262.9 1034.02   276.6  1030.9
   303.9 1023.78   317.6 1018.65     345 1001.17   394.3   973.6   454.4  960.63
     493  956.54   495.4  956.39     508  957.35   516.1  960.05   604.9  1005.1
   623.9 1013.52   741.7  1026.1   755.4 1029.87   823.8 1062.12   855.4 1079.58
   878.5 1095.46   919.5 1127.59   942.4  1142.7   959.8 1148.74    1001 1158.45
#Mann= 3 , 0 , 0
       0      .1       0     493    .045       0     508      .1       0
Bank Sta=493,508
XS Rating Curve= 0 ,0
Exp/Cntr=0.3,0.1

Type RM Length L Ch R = 1 ,147.9   ,147.202,147.918,148.698
XS GIS Cut Line= 3
     1705799.881      307482.773     1705412.256      307166.149
     1705023.642      306850.747
#Sta/Elev= 30
       0  992.79    63.9  991.48   184.7  990.58   201.9  989.67   257.5  984.35
   276.3  983.54   309.2  985.19   339.9  988.25   370.5  989.36   385.9  986.49
   462.5  960.71   482.7  952.33     491  949.51   500.5  948.35     506  948.45
   523.8  950.46   572.9  953.23   615.5  952.23   630.8  953.87   646.1  960.15
   665.7  970.16   689.9  980.78   708.7  985.56   727.6  987.28   753.1  987.73
   784.1   989.5   840.6  991.07   876.7  993.54   951.9 1000.47    1001 1004.01
#Mann= 3 , 0 , 0
       0      .1       0     491    .045       0     506      .1       0
Bank Sta=491,506
XS Rating Curve= 0 ,0
Exp/Cntr=0.3,0.1

Chan Stop Cuts=-1
Use User Specified Reach Order=0